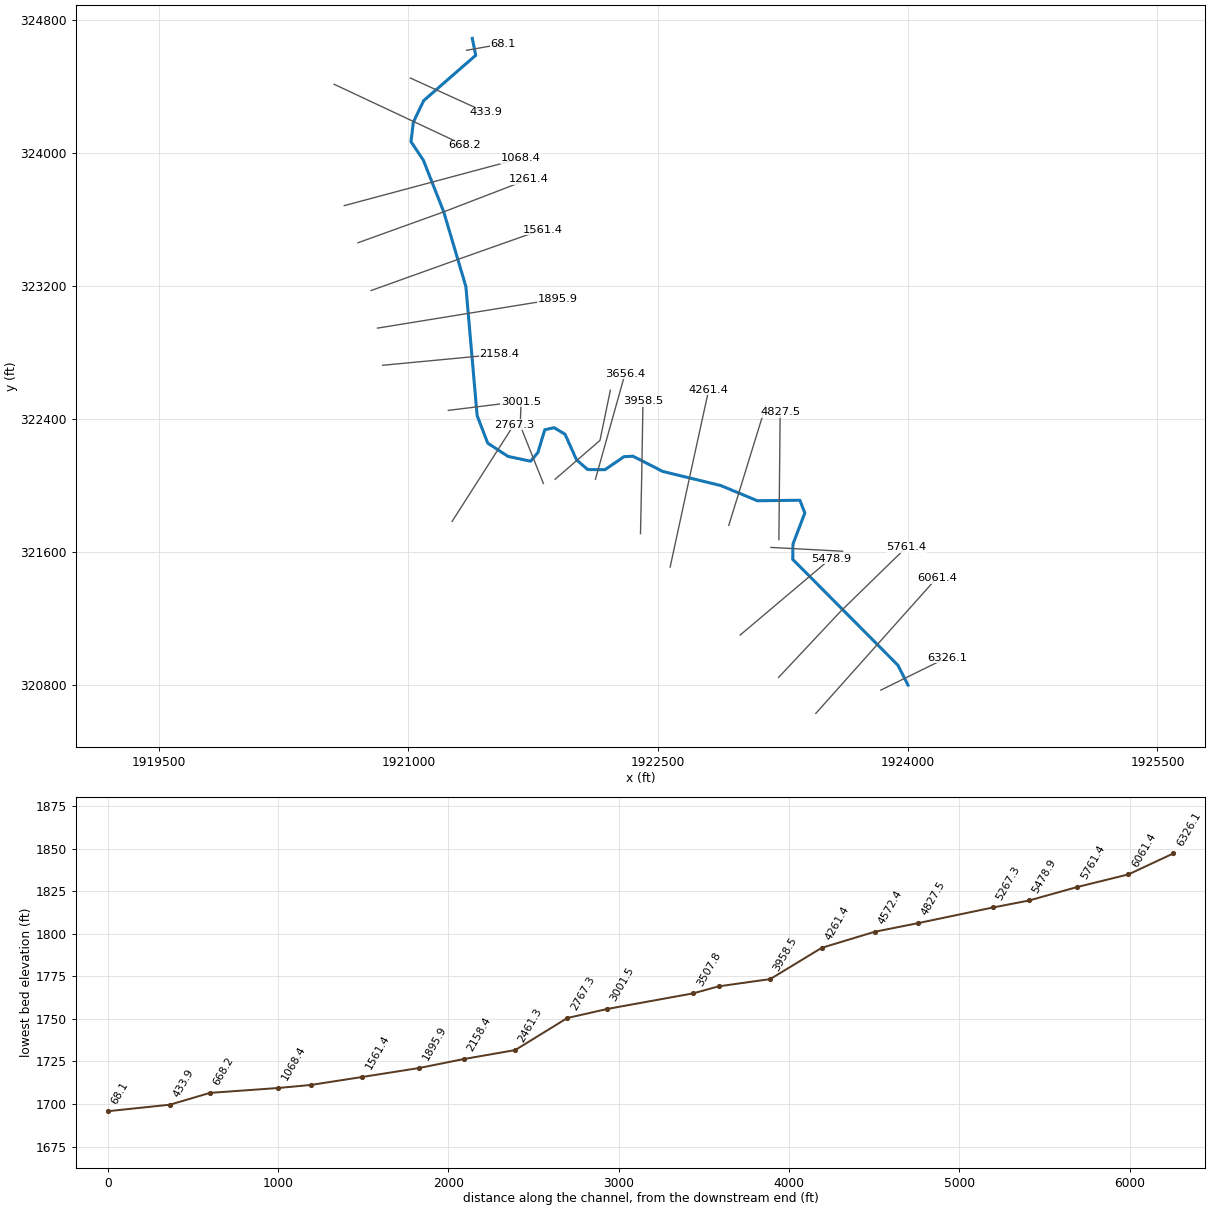
--- MillCreek.prj (project) ---

Proj Title=MillCreek
Current Plan=p01
Default Exp/Contr=0,0
English Units
Geom File=g01
Flow File=f01
Plan File=p01
BEGIN DESCRIPTION:
END DESCRIPTION:
DSS Export Rating Curves= 0
DSS Export Rating Curve Sorted= 0
DSS Export Volume Flow Curves= 0
DXF OffsetX= 0
DXF OffsetY= 0
DXF ScaleX= 0
DXF ScaleY= 0

--- MillCreek.p01 (plan) ---

Plan Title=Floodplain
Program Version=4.00
Geom File=g01
Flow File=f01
K Sum by GR=0
Std Step Tol=0.01
Critical Tol=0.01
Num of Std Step Trials=20
Max Error Tol=0.3
Flow Tol Ratio=0.001
Split Flow NTrial=30
Split Flow Tol=0.02
Split Flow Ratio=0.02
Log Output Level=0
Friction Slope Method=1
Unsteady Friction Slope Method=2
Unsteady Bridges Friction Slope Method=1
Global Log Level=0
CheckData=False
Run HTab=0
Run UNet=0
Run PostProcess=0
UNET Theta=0
UNET Theta Warmup=0
UNET ZTol=0
UNET ZSATol=0
UNET MxIter=0
UNET MaxInSteps=0
UNET DtIC=0
UNET DtMin=0
UNET MaxCRTS=0
UNET WFStab=0
UNET SFStab=0
UNET WFX=0
UNET SFX=0
UNET DSS MLevel=0
UNET DZMax Abort=0
UNET Convert EG Bridges=0
UNET Use Existing IB Tables=0
UNET Froude Limit=0
UNET Froude Power=0
Write IC File=0
Echo Input=False
Echo Output=False
Write Detailed=0

--- MillCreek.f01 (steady flow) ---

Flow Title=NFF Regression Equation
Program Version=4.00
Number of Profiles=1
Profile Names=P100yr
River Rch & RM=MillCreek,Main      ,6326.1
1314.425
River Rch & RM=MillCreek,Main      ,3958.5
1340.929
River Rch & RM=MillCreek,Main      ,2461.3
1488.646
River Rch & RM=MillCreek,Main      ,68.1
1532.914
Boundary for River Rch & Prof#=MillCreek,Main      ,1
Up Type=0
Dn Type=3
Dn Slope=0.015744

--- MillCreek.g01 (geometry) ---

Geom Title=USGS 3m DEM
Program Version=4.10

River Reach=MillCreek       ,Main
Reach XY= 30
     1924001.171      320797.731     1923940.407      320917.523
     1923308.463      321554.675      1923309.97      321647.028
      1923381.38      321834.189     1923351.312      321910.632
      1923096.32      321907.571     1922876.171       321999.12
     1922527.213      322084.189     1922348.513      322175.833
     1922294.574      322172.731     1922180.806      322094.668
      1922076.84      322095.421     1922009.852      322153.634
     1921940.407      322308.147     1921875.349      322347.242
     1921818.961      322335.377     1921777.213      322197.036
      1921733.27      322145.482     1921598.393      322174.467
     1921476.183      322254.223     1921412.381      322420.194
     1921344.921      323197.036      1921211.24      323648.425
      1921089.11      323958.442      1921015.06      324069.538
     1921029.217      324186.915     1921091.449      324316.828
     1921403.949      324589.397     1921383.292      324691.579

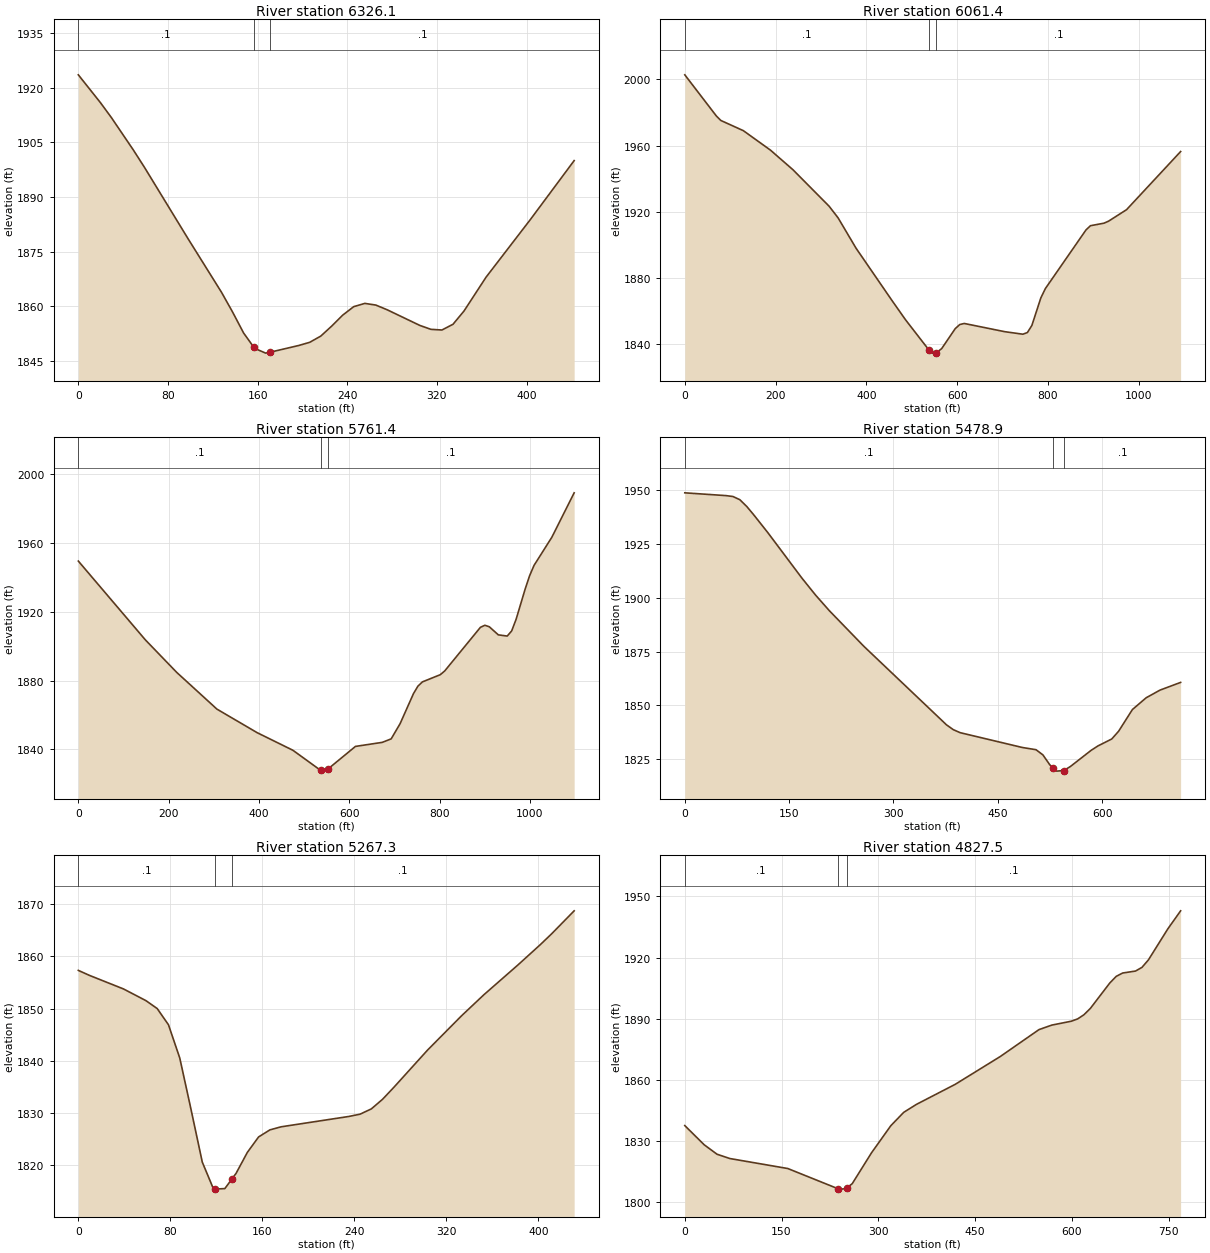
Type RM Length L Ch R = 1 ,6326.1  ,256,264.7,273.4
XS GIS Cut Line= 2
     1923837.762      320767.524     1924234.699      320963.158
#Sta/Elev= 30
       0 1923.57    19.7 1915.94    29.5 1911.83    49.2 1902.88      59 1898.17
    98.3 1878.37   127.8 1863.83   137.7  1858.4   147.5 1852.66   156.4 1848.83
   157.3 1848.44   167.2 1847.13   171.4  1847.4   196.7 1849.23   206.5  1850.1
   216.4 1851.81   226.2 1854.58     236 1857.58   245.8  1859.9   255.7 1860.79
   265.5 1860.33   275.4 1859.07   304.8 1854.74   314.7 1853.66   324.5 1853.48
   334.4 1855.06   344.2  1858.7   363.9    1868   403.2 1883.73   442.5 1900.01
#Mann= 3 , 0 , 0
       0      .1       0   156.4    .045       0   171.4      .1       0
Bank Sta=156.4,171.4
XS Rating Curve= 0 ,0
Exp/Cntr=0.3,0.1

Type RM Length L Ch R = 1 ,6061.4  ,300.5,300,298.5
XS GIS Cut Line= 3
     1923447.403      320627.426     1923810.695      321035.022
     1924173.988      321442.618
#Sta/Elev= 30
       0 2002.77    69.5 1977.93    79.4 1975.22     129 1969.06   188.6 1957.33
   238.2 1945.48   317.7  1923.5   337.5 1916.48   377.2  1898.1   456.6 1866.43
   486.4 1854.81   538.5 1836.39     546 1834.78   553.5 1834.88   565.8 1837.53
   595.6 1849.56   605.6 1852.04   615.5 1852.68   704.8 1847.72   744.6  1846.2
   754.5  1847.2   764.4 1851.49   784.2 1868.16   794.2 1873.78   883.5 1909.11
   893.4 1911.69   923.2 1913.22   933.2 1914.42   972.9 1921.36    1092 1956.46
#Mann= 3 , 0 , 0
       0      .1       0   538.5    .045       0   553.5      .1       0
Bank Sta=538.5,553.5
XS Rating Curve= 0 ,0
Exp/Cntr=0.3,0.1

Type RM Length L Ch R = 1 ,5761.4  ,285,282.5,280.9
XS GIS Cut Line= 3
     1923223.587      320843.957      1923595.87      321241.439
     1923991.926        321628.3
#Sta/Elev= 30
       0 1949.33   148.5 1903.58   217.8 1884.75     307 1863.39   396.1 1849.72
   475.3  1839.5   537.1 1827.77   544.6  1827.4   552.1 1828.45   613.8 1841.75
   673.1 1844.09   692.9 1846.12   712.7 1854.95   742.3 1872.38   752.2 1876.74
   762.1  1879.2   801.6 1883.37   811.5 1885.55   890.6 1910.88   900.5 1912.08
   910.4 1911.17   930.2 1906.51   949.9  1905.8   959.8 1908.78   969.7 1915.59
   989.5 1932.94   999.4 1940.73  1009.3 1946.81  1048.8 1963.17  1098.2 1988.95
#Mann= 3 , 0 , 0
       0      .1       0   537.1    .045       0   552.1      .1       0
Bank Sta=537.1,552.1
XS Rating Curve= 0 ,0
Exp/Cntr=0.3,0.1

Type RM Length L Ch R = 1 ,5478.9  ,228.8,211.7,194.5
XS GIS Cut Line= 2
     1922992.807      321098.977      1923536.87      321559.626
#Sta/Elev= 30
       0 1948.78    59.4 1947.48    69.3 1947.06    79.2 1945.57    89.1 1942.43
      99 1938.61   118.8 1930.53   168.3  1909.2   188.1 1901.24   207.9    1894
   257.4 1877.49   376.2 1841.01   386.1 1838.73     396 1837.34   485.2 1830.47
     505 1829.43   514.9 1827.02   524.8 1822.42   530.1 1820.85   534.7 1819.48
   545.1 1819.77   554.5 1821.65   584.2 1829.13   594.1  1831.2   613.9 1834.42
   623.8 1838.03   643.6  1848.1   663.4 1853.57   683.2 1857.11   712.9  1860.7
#Mann= 3 , 0 , 0
       0      .1       0   530.1    .045       0   545.1      .1       0
Bank Sta=530.1,545.1
XS Rating Curve= 0 ,0
Exp/Cntr=0.3,0.1

Type RM Length L Ch R = 1 ,5267.3  ,402.9,439.7,476.5
XS GIS Cut Line= 2
       1923177.5      321626.609     1923608.106      321603.572
#Sta/Elev= 30
       0 1857.33     9.8 1856.36    39.2 1853.78    58.8 1851.53    68.6 1850.01
    78.4  1846.9    88.2 1840.54      98 1830.68   107.8 1820.57   117.6 1815.39
   118.6  1815.4   127.4 1815.49   133.6 1817.34   137.2 1818.42     147 1822.44
   156.8  1825.4   166.6 1826.75   176.4 1827.34   235.2 1829.32     245 1829.76
   254.8 1830.77   264.6 1832.62   274.4 1834.91   303.8 1842.07   333.2 1848.61
   352.8 1852.68   382.2 1858.35   401.8 1862.27   411.6 1864.34   431.2 1868.75
#Mann= 3 , 0 , 0
       0      .1       0   118.6    .045       0   133.6      .1       0
Bank Sta=118.6,133.6
XS Rating Curve= 0 ,0
Exp/Cntr=0.3,0.1

Type RM Length L Ch R = 1 ,4827.5  ,261.6,255,248.5
XS GIS Cut Line= 2
     1923225.345      321673.391     1923233.061      322442.037
#Sta/Elev= 30
       0 1837.42      30 1828.01    49.9 1823.36    69.9 1821.23   159.7 1816.32
   236.9 1806.48   239.6  1806.2   249.6 1806.39   251.9 1806.96   259.6 1808.89
   289.5 1824.06   319.4 1837.36   339.4 1843.93   359.4 1847.89   419.3  1857.7
   489.2 1871.38   549.1 1884.58     569  1886.8     599 1888.69     609 1889.83
   618.9 1891.91   628.9 1895.05   658.9 1907.49   668.9 1910.75   678.8 1912.39
   698.8 1913.36   708.8 1915.17   718.8 1918.85   748.7    1934   768.7 1942.95
#Mann= 3 , 0 , 0
       0      .1       0   236.9    .045       0   251.9      .1       0
Bank Sta=236.9,251.9
XS Rating Curve= 0 ,0
Exp/Cntr=0.3,0.1

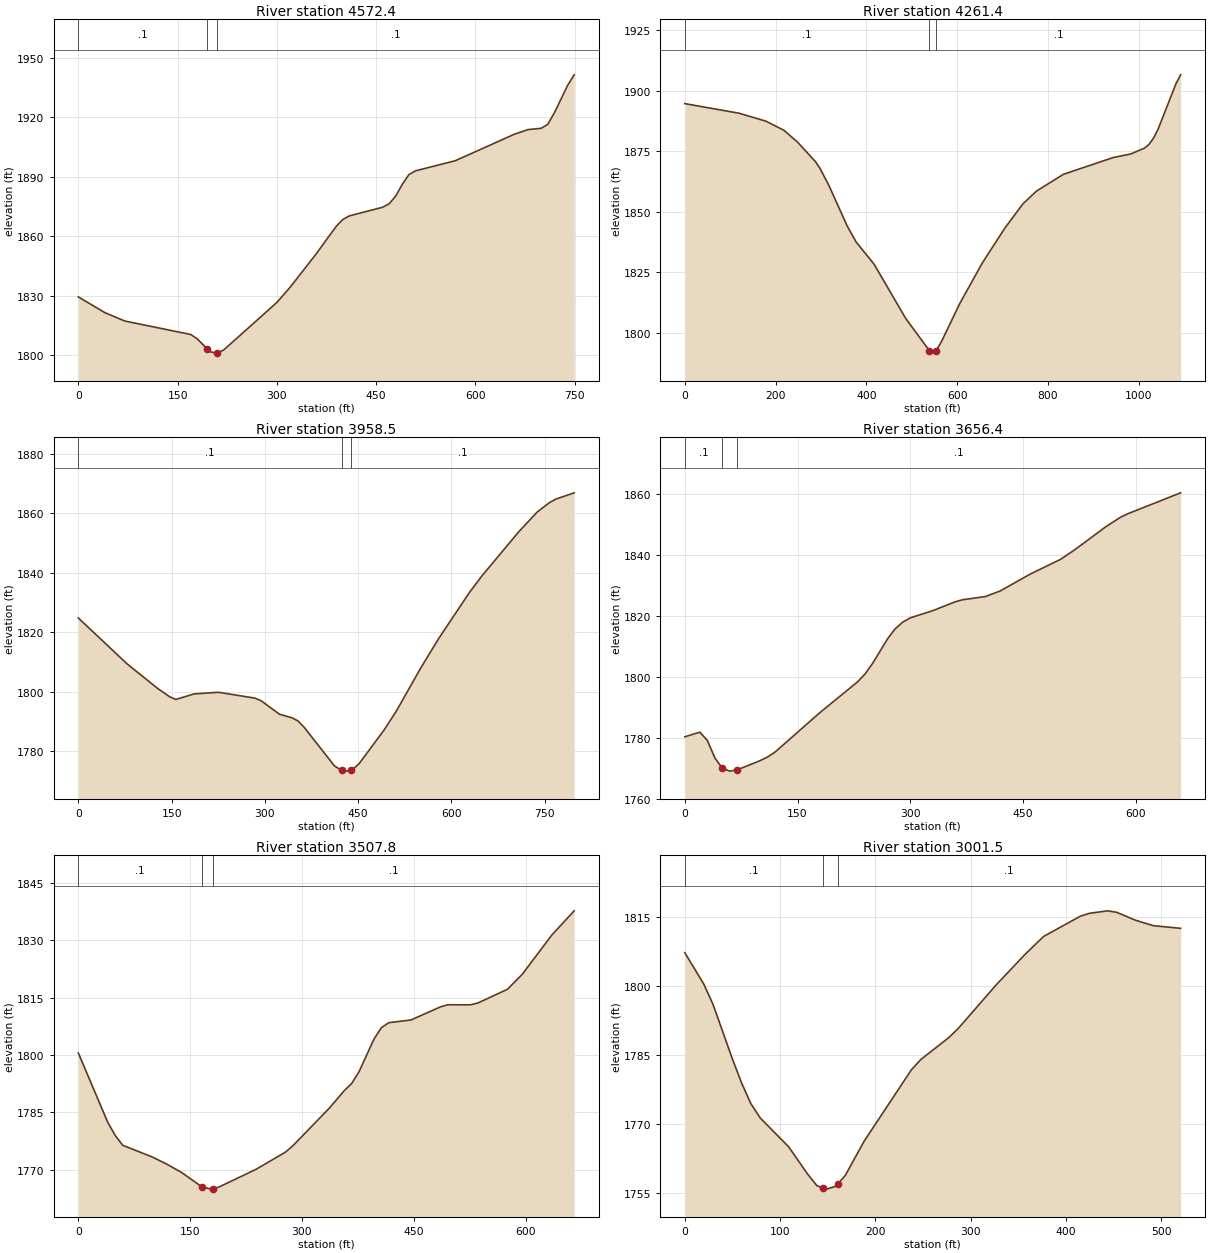
Type RM Length L Ch R = 1 ,4572.4  ,309.1,311,312.9
XS GIS Cut Line= 2
     1922924.453      321759.512     1923144.914      322475.573
#Sta/Elev= 30
       0 1829.45      40 1821.55    69.9 1817.32   169.8 1810.51   179.8 1808.28
     195 1803.18   199.8 1801.74   209.8 1801.11     210 1801.14   219.8 1802.74
   299.7 1826.57   319.7 1834.17   359.6 1851.23   389.6    1865   399.6 1868.48
   409.6 1870.31   459.5 1874.62   469.5 1876.34   479.5 1880.26   489.5 1886.18
   499.5 1891.11   509.5 1893.02   569.4 1898.09   659.3 1911.52   679.3 1913.78
   699.3 1914.45   709.3 1916.43   719.3 1922.25   739.2    1936   749.2 1941.41
#Mann= 3 , 0 , 0
       0      .1       0     195    .045       0     210      .1       0
Bank Sta=195,210
XS Rating Curve= 0 ,0
Exp/Cntr=0.3,0.1

Type RM Length L Ch R = 1 ,4261.4  ,296.8,302.7,308.7
XS GIS Cut Line= 3
     1922571.943      321508.019     1922687.332      322041.686
      1922803.71       322575.14
#Sta/Elev= 30
       0 1894.67   119.1 1890.73   178.7 1887.43   218.4 1883.66   248.2  1878.8
   287.9 1870.71   297.8 1867.94   317.7 1860.77   357.4 1844.26   377.2  1837.6
     417 1828.37   486.4 1806.05   538.5 1792.77     546 1791.69   553.5 1792.65
   565.8 1796.65   605.6 1812.17   655.2 1828.88   704.8 1843.27   744.6 1853.28
   774.3 1858.54   833.9  1865.5   943.1 1872.39   982.8 1873.93  1012.6 1876.32
  1022.5 1877.88  1032.4 1880.46  1042.4 1884.15  1082.1 1903.05    1092 1906.56
#Mann= 3 , 0 , 0
       0      .1       0   538.5    .045       0   553.5      .1       0
Bank Sta=538.5,553.5
XS Rating Curve= 0 ,0
Exp/Cntr=0.3,0.1

Type RM Length L Ch R = 1 ,3958.5  ,309.2,302.1,294.9
XS GIS Cut Line= 3
     1922393.904       321709.54     1922401.347      322062.531
      1922408.79      322506.958
#Sta/Elev= 30
       0  1824.8    78.5 1809.36   127.5 1801.13   147.1  1798.3   156.9 1797.41
   186.3 1799.28   225.6 1799.82   284.4 1797.85   294.2 1796.95   323.6 1792.45
   343.3 1791.28   353.1 1790.23     363 1788.12   412.3 1775.01   423.7 1773.59
   432.1 1773.32   438.7 1773.78     442 1774.01   451.8 1775.86   491.4 1787.02
   511.1 1793.34   550.6  1807.9   580.2 1818.06   629.6  1833.5   649.4 1838.98
   708.7 1853.82   738.3 1860.44     758 1863.58   767.9 1864.72   797.6 1866.86
#Mann= 3 , 0 , 0
       0      .1       0   423.7    .045       0   438.7      .1       0
Bank Sta=423.7,438.7
XS Rating Curve= 0 ,0
Exp/Cntr=0.3,0.1

Type RM Length L Ch R = 1 ,3656.4  ,161.7,148.6,135.5
XS GIS Cut Line= 2
     1922123.204      322037.094     1922300.942      322672.414
#Sta/Elev= 30
       0 1780.34      20 1781.85      30 1779.16      40 1773.41      50 1770.01
      60 1769.08      70 1769.52     100  1772.5     110 1773.67     120 1775.31
   179.9  1788.3   229.9 1798.35   239.9 1800.96   249.9 1804.42   269.9 1812.51
   279.9 1815.74   289.9 1817.93   299.9 1819.32   329.9 1821.69   359.8 1824.61
   369.8 1825.28   399.8 1826.31   419.8 1828.17   459.8 1833.72   499.8 1838.49
   519.8 1841.82   559.8 1849.15   579.8 1852.34   589.7  1853.5   659.7 1860.33
#Mann= 3 , 0 , 0
       0      .1       0      50    .045       0      70      .1       0
Bank Sta=50,70
XS Rating Curve= 0 ,0
Exp/Cntr=0.3,0.1

Type RM Length L Ch R = 1 ,3507.8  ,478.2,506.3,532.4
XS GIS Cut Line= 3
     1921881.076      322037.013     1922150.426      322270.922
     1922212.802      322572.878
#Sta/Elev= 30
       0 1800.55    39.6 1782.37    49.6 1778.97    59.5 1776.44    99.1 1773.38
   118.9 1771.48   138.7 1769.31   165.9 1765.56   178.4 1764.98   180.9 1765.11
   188.3  1765.5   237.8 1770.09   277.5  1774.6   287.4 1776.23   336.9 1786.18
   356.7  1790.7   366.7 1792.59   376.6 1795.67   396.5 1804.14   406.5 1807.16
   416.4 1808.46   446.2 1809.17     486 1812.61     496 1813.15   525.8 1813.12
   535.8 1813.59   575.6 1817.18   595.4 1821.08   635.2 1831.37   665.1 1837.68
#Mann= 3 , 0 , 0
       0      .1       0   165.9    .045       0   180.9      .1       0
Bank Sta=165.9,180.9
XS Rating Curve= 0 ,0
Exp/Cntr=0.3,0.1

Type RM Length L Ch R = 1 ,3001.5  ,255.6,234.1,214.4
XS GIS Cut Line= 3
     1921810.549      322011.496      1921671.31      322361.097
     1921676.583      322504.831
#Sta/Elev= 30
       0 1807.22    19.8 1800.44    29.7 1795.93    49.5 1784.36    59.4 1778.97
    69.3 1774.37    79.2 1771.25   108.9    1765   128.7 1759.09   138.6 1756.53
   145.3 1756.02   148.5 1755.78   158.4  1756.4   160.3 1756.85   168.4 1758.78
   188.2 1766.24   237.7 1781.74   247.6 1783.98   277.3 1788.81   287.2 1790.82
   326.8 1800.26   356.5 1806.77   376.3 1810.74   414.7 1815.14   424.2 1815.78
   443.4 1816.33     453 1816.01   472.2 1814.33   491.4  1813.1   520.1 1812.52
#Mann= 3 , 0 , 0
       0      .1       0   145.3    .045       0   160.3      .1       0
Bank Sta=145.3,160.3
XS Rating Curve= 0 ,0
Exp/Cntr=0.3,0.1

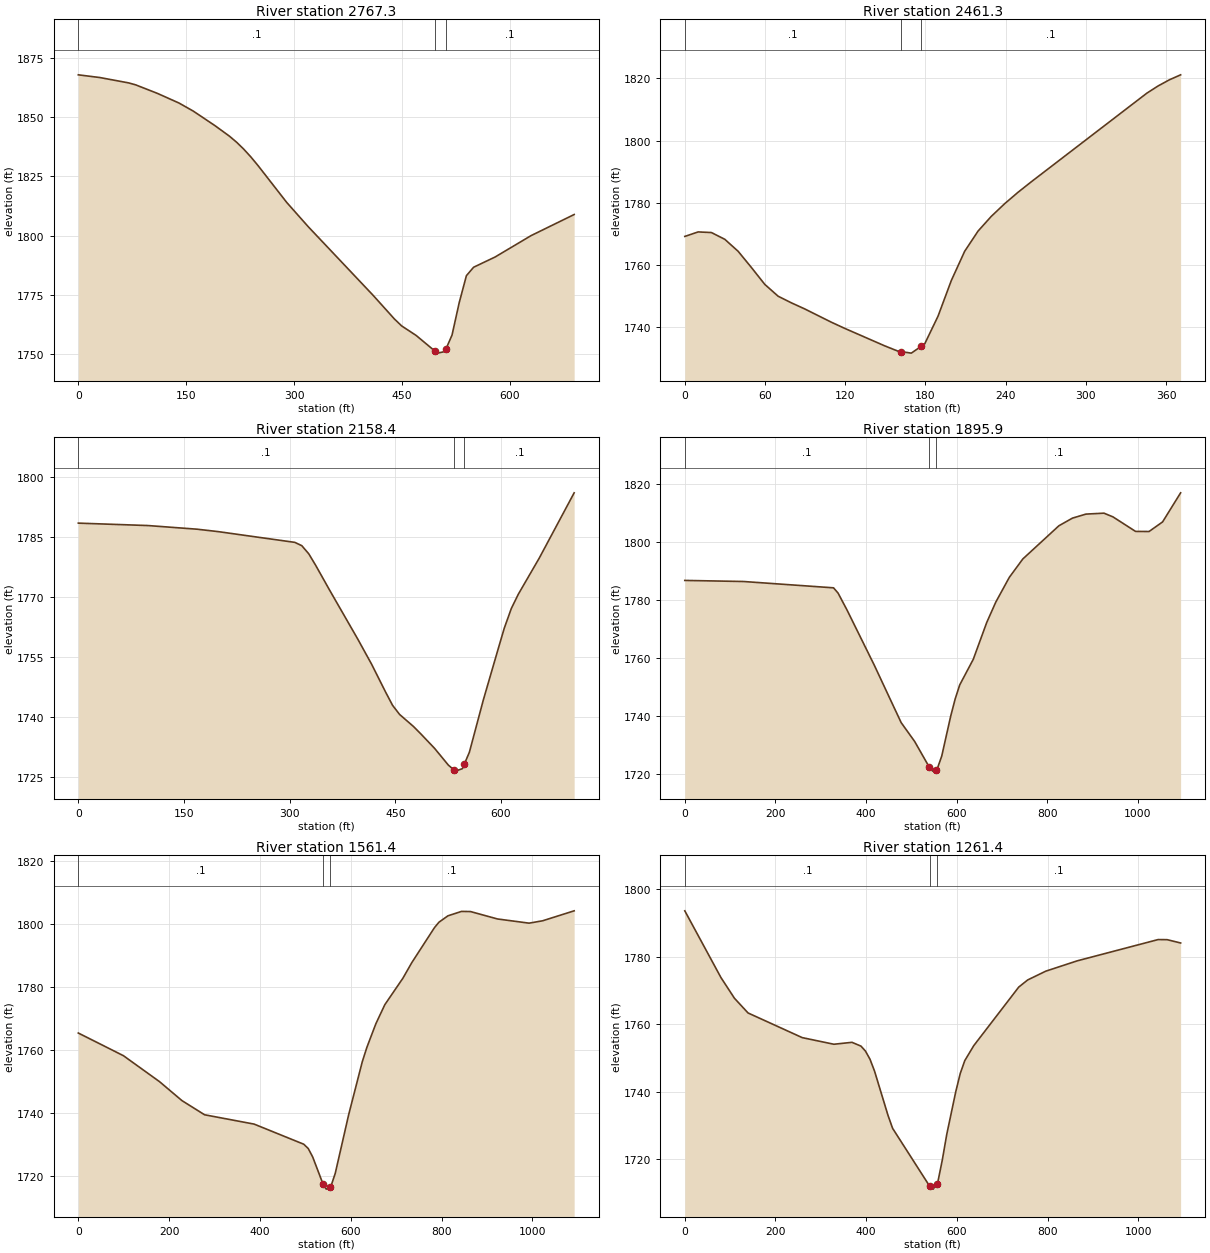
Type RM Length L Ch R = 1 ,2767.3  ,325.9,305.9,286
XS GIS Cut Line= 2
     1921262.142      321783.419     1921632.991      322364.486
#Sta/Elev= 30
       0 1867.85      30  1866.7    69.9 1864.45    79.9  1863.6   109.9 1860.03
   139.9 1855.96   159.8 1852.55   189.8 1846.45   209.8 1842.04   219.8 1839.49
   229.8 1836.55   239.8 1833.24   249.8 1829.58   289.7 1814.03   319.7 1803.77
   409.6 1774.92   439.6 1764.82   449.6 1761.92   469.5 1757.96   496.1 1751.24
   499.5 1750.47   509.5 1751.13   511.1 1752.24   519.5 1758.07   529.5 1771.74
   539.5 1783.13   549.5 1786.69   579.4 1791.01   629.4 1800.03   689.3 1808.93
#Mann= 3 , 0 , 0
       0      .1       0   496.1    .045       0   511.1      .1       0
Bank Sta=496.1,511.1
XS Rating Curve= 0 ,0
Exp/Cntr=0.3,0.1

Type RM Length L Ch R = 1 ,2461.3  ,303.5,302.8,302.2
XS GIS Cut Line= 3
     1921239.598       322451.67     1921566.008      322492.073
     1921603.221      322511.211
#Sta/Elev= 30
       0 1769.16      10 1770.61    19.9 1770.41    29.9 1768.24    39.9 1764.38
    49.8 1759.18    59.8 1753.75    69.8 1749.94    79.7 1747.81    89.7 1745.85
   109.6 1741.58   119.6  1739.6   149.5 1733.98   159.5 1732.26   161.7 1732.12
   169.4 1731.64   176.7  1733.8   179.4  1734.6   189.4 1743.54   199.3 1754.97
   209.3 1764.38   219.3 1770.87   229.2 1775.61   239.2 1779.68   249.2 1783.35
   259.1 1786.72   345.6 1815.24     354 1817.55   362.4 1819.52   370.8 1821.12
#Mann= 3 , 0 , 0
       0      .1       0   161.7    .045       0   176.7      .1       0
Bank Sta=161.7,176.7
XS Rating Curve= 0 ,0
Exp/Cntr=0.3,0.1

Type RM Length L Ch R = 1 ,2158.4  ,261,262.5,264
XS GIS Cut Line= 2
     1920845.191      322723.193     1921545.807      322789.775
#Sta/Elev= 30
       0 1788.48    99.1 1787.87   168.5 1786.96   198.2 1786.36   307.3 1783.66
   317.2 1782.83   327.1 1780.79     337 1777.88   356.8 1771.66   396.5 1759.48
   416.3 1753.14   436.1 1746.18     446 1742.86     456 1740.56   475.8 1737.53
   485.7 1735.77   505.5  1732.1   525.4 1727.84   533.1 1726.69   535.3 1726.36
   545.2 1726.98   548.1 1728.19   555.1  1731.1   574.9  1744.2   594.7 1756.22
   604.6 1762.16   614.6 1767.09   624.5 1770.66   654.2  1779.7   703.8 1796.07
#Mann= 3 , 0 , 0
       0      .1       0   533.1    .045       0   548.1      .1       0
Bank Sta=533.1,548.1
XS Rating Curve= 0 ,0
Exp/Cntr=0.3,0.1

Type RM Length L Ch R = 1 ,1895.9  ,330.2,334.4,338.4
XS GIS Cut Line= 2
      1920813.86      322946.913     1921894.126      323122.701
#Sta/Elev= 30
       0 1786.79   129.4 1786.42   328.3 1784.24   338.3 1782.44   358.2 1776.57
   417.9 1757.71   477.6 1737.81   507.4 1731.31   539.5 1722.51   547.2 1721.09
   554.5 1721.64   557.2 1721.85   567.1 1726.22     587 1740.06     597 1746.04
   606.9  1750.8   636.8 1759.62   666.6 1772.34   686.5 1779.32   716.4 1787.86
   746.2 1794.19   825.8 1805.62   855.7 1808.25   885.5 1809.64   925.3 1809.96
   945.2 1808.68     995 1803.68  1024.8 1803.64  1054.7 1806.95  1094.5 1816.97
#Mann= 3 , 0 , 0
       0      .1       0   539.5    .045       0   554.5      .1       0
Bank Sta=539.5,554.5
XS Rating Curve= 0 ,0
Exp/Cntr=0.3,0.1

Type RM Length L Ch R = 1 ,1561.4  ,299.9,300,300.6
XS GIS Cut Line= 3
     1920775.376      323173.302     1921289.267      323357.777
     1921803.903      323540.182
#Sta/Elev= 30
       0 1765.44    99.3 1758.24   178.7    1750   228.3 1743.95     278 1739.46
   387.2 1736.49   496.4  1730.1   506.3 1728.74   516.2 1726.03   538.5 1717.59
     546 1715.82   553.5 1716.38   555.9 1716.56   565.8 1720.81   595.6  1739.6
   625.4 1756.33   635.4 1760.85   655.2 1768.37     675 1774.45   714.8 1782.86
   734.6 1787.86   784.3 1798.93   794.2 1800.67     814  1802.7   843.8  1804.1
   863.7 1804.06   923.2  1801.7   992.7 1800.37  1022.5 1801.12    1092 1804.29
#Mann= 3 , 0 , 0
       0      .1       0   538.5    .045       0   553.5      .1       0
Bank Sta=538.5,553.5
XS Rating Curve= 0 ,0
Exp/Cntr=0.3,0.1

Type RM Length L Ch R = 1 ,1261.4  ,194.9,193,190.6
XS GIS Cut Line= 3
     1920696.416      323460.785      1921211.81      323646.832
     1921720.809      323843.003
#Sta/Elev= 30
       0 1793.55    79.7  1773.8   109.6 1767.65   139.5 1763.31     259 1756.01
   328.8 1754.05   368.6 1754.62   388.5  1753.5   398.5 1752.01   408.5 1749.59
   418.4 1746.11   448.3 1732.92   458.3 1729.15   540.4 1711.94   547.9 1711.16
   555.4 1712.68   557.9 1713.19   567.8 1719.74   577.7 1727.39   597.5 1739.99
   607.4 1745.38   617.4  1749.2   637.2 1753.63   736.4 1770.97   756.2 1773.09
   795.9 1775.68   865.3 1778.74  1043.8 1785.04  1063.7 1785.01  1093.4 1784.03
#Mann= 3 , 0 , 0
       0      .1       0   540.4    .045       0   555.4      .1       0
Bank Sta=540.4,555.4
XS Rating Curve= 0 ,0
Exp/Cntr=0.3,0.1

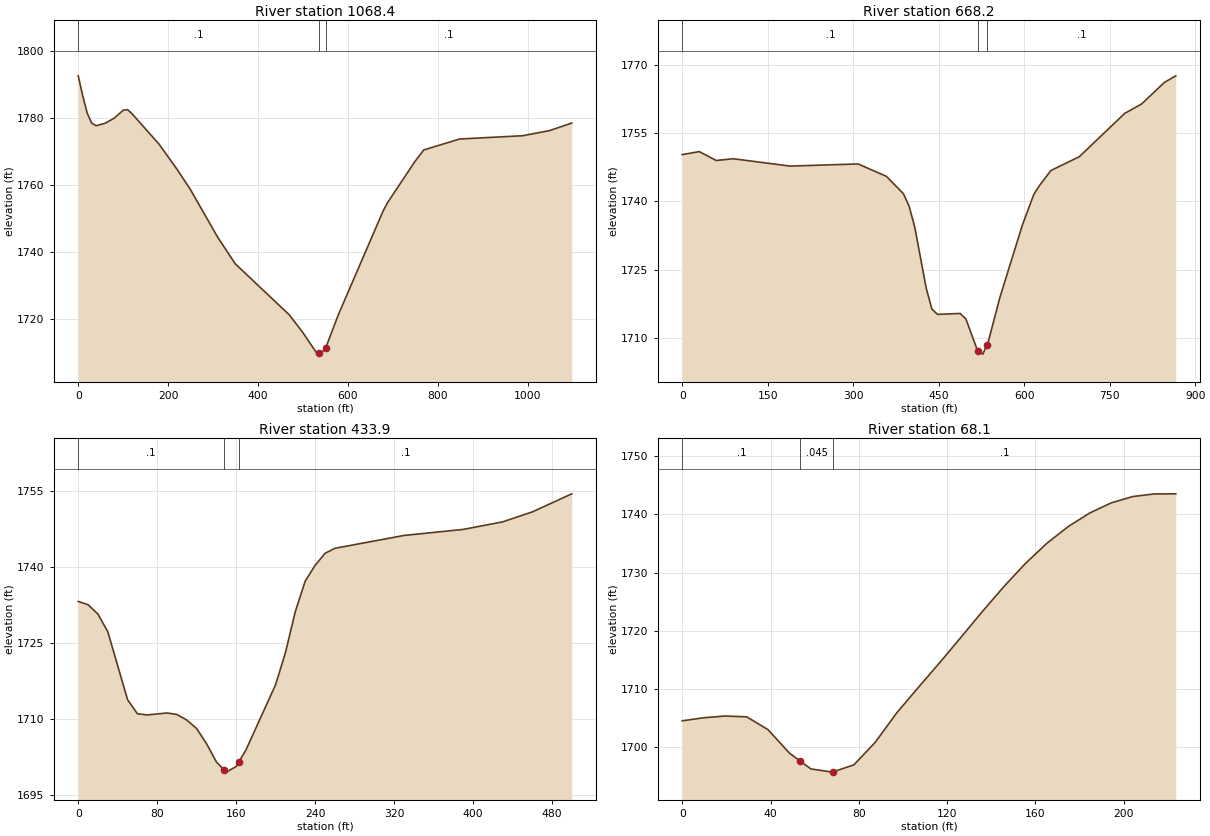
Type RM Length L Ch R = 1 ,1068.4  ,415.8,399.8,383.9
XS GIS Cut Line= 2
     1920614.156      323684.351     1921675.153      323968.974
#Sta/Elev= 30
       0  1792.7      10 1786.74      20 1781.54      30 1778.55      40 1777.76
    59.9  1778.5    79.9    1780    99.9 1782.39   109.8 1782.58   119.8 1781.34
   179.8 1772.26   219.7 1764.76   249.7 1758.66   309.6 1744.55   349.5 1736.41
   469.4 1721.18   499.3 1715.95   529.3 1709.99   535.9 1709.58   539.3 1709.37
   550.9 1711.28   579.2 1721.25   679.1 1752.38   689.1 1754.86     749 1766.97
     769  1770.5   848.8 1773.78   988.7 1774.76  1048.6 1776.28  1098.5 1778.56
#Mann= 3 , 0 , 0
       0      .1       0   535.9    .045       0   550.9      .1       0
Bank Sta=535.9,550.9
XS Rating Curve= 0 ,0
Exp/Cntr=0.3,0.1

Type RM Length L Ch R = 1 ,668.2   ,233.6,234.3,235
XS GIS Cut Line= 2
     1920553.675      324414.833     1921337.415      324046.505
#Sta/Elev= 30
       0 1750.27    29.9 1750.93    59.7 1748.98    89.6 1749.36   189.1 1747.75
   308.6 1748.22   358.3  1745.5   388.2 1741.68   398.2 1738.92   408.1 1734.31
     428 1721.04     438 1716.41   447.9 1715.22   487.7 1715.42   497.7 1714.23
   517.6 1707.46   519.6 1707.27   527.6  1706.5   534.6 1708.59   537.5 1709.45
   557.4 1718.94   597.2 1734.95   617.1 1741.59   627.1 1743.52     647 1746.79
   696.8 1749.81   776.4 1759.31   806.2 1761.39   846.1 1766.11     866 1767.55
#Mann= 3 , 0 , 0
       0      .1       0   519.6    .045       0   534.6      .1       0
Bank Sta=519.6,534.6
XS Rating Curve= 0 ,0
Exp/Cntr=0.3,0.1

Type RM Length L Ch R = 1 ,433.9   ,352.4,365.8,379.1
XS GIS Cut Line= 2
     1921011.005      324452.657     1921466.065      324245.328
#Sta/Elev= 30
       0 1733.19      10 1732.54      20  1730.7      30 1727.21      50 1713.85
      60 1711.07      70 1710.84      90 1711.23     100 1710.93     110 1709.84
     120 1708.16     130  1705.2     140 1701.59   147.9    1700     150 1699.58
     160 1700.68   162.9 1701.63     170 1703.96     200  1716.8     210 1723.14
     220 1731.23     230 1737.19     240 1740.29     250 1742.65     260 1743.65
     330 1746.18     390 1747.37   430.1 1748.86   460.1 1750.82   500.1 1754.38
#Mann= 3 , 0 , 0
       0      .1       0   147.9    .045       0   162.9      .1       0
Bank Sta=147.9,162.9
XS Rating Curve= 0 ,0
Exp/Cntr=0.3,0.1

Type RM Length L Ch R = 1 ,68.1    ,58.4,68.1,77.8
XS GIS Cut Line= 2
      1921349.11      324619.583     1921569.198      324658.922
#Sta/Elev= 26
       0 1704.55     9.7 1705.07    19.4 1705.37    29.2 1705.23    38.9 1703.03
    48.6 1698.99    53.5 1697.62    58.3 1696.28      68 1695.73    68.5 1695.79
    77.8 1696.99    87.5 1700.88    97.2 1705.92   106.9 1710.25   116.6 1714.52
   126.4 1718.95   136.1 1723.38   145.8 1727.64   155.5 1731.59   165.2 1735.05
     175 1737.96   184.7 1740.27   194.4    1742   204.1 1743.08   213.8 1743.53
   223.6 1743.55
#Mann= 3 , 0 , 0
       0      .1       0    53.5    .045       0    68.5      .1       0
Bank Sta=53.5,68.5
XS Rating Curve= 0 ,0
Exp/Cntr=0.3,0.1

Chan Stop Cuts=-1
Use User Specified Reach Order=0
Composite Channel Slope=5